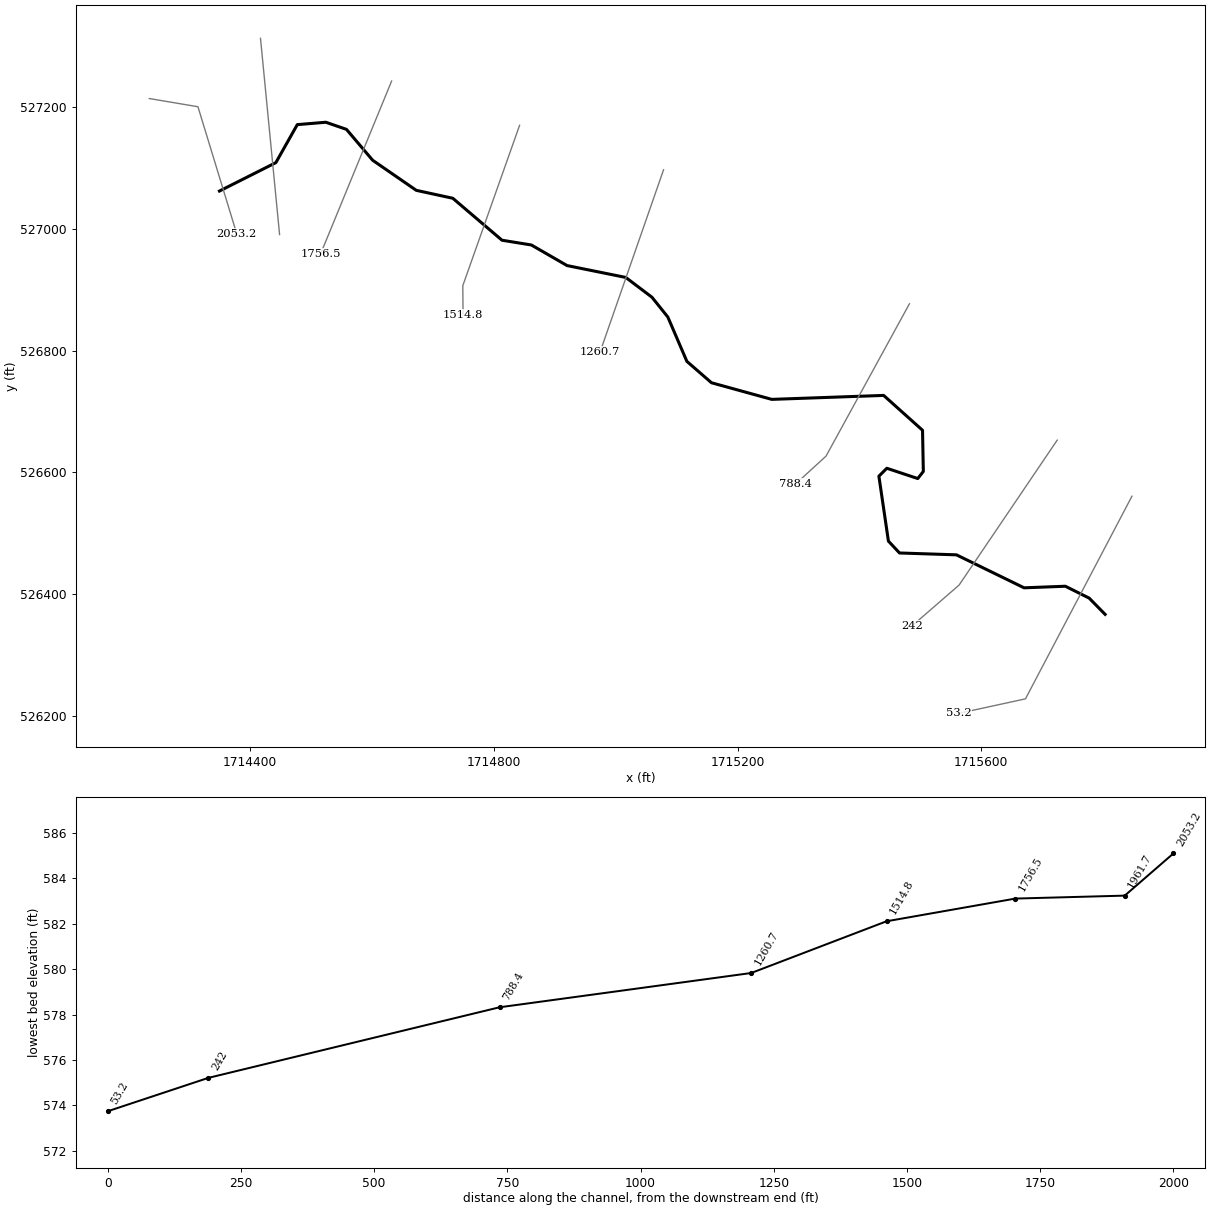
--- NP11.prj (project) ---

Proj Title=NP11
Current Plan=p01
Default Exp/Contr=0,0
English Units
Geom File=g01
Flow File=f01
Plan File=p01
BEGIN DESCRIPTION:
AMEC Environment & Infrastructure, 2013
Projection: NAD 1983 State Plane West Virginia South FIPS 4702 (US Feet)
Vertical Datum: NAVD 1988
END DESCRIPTION:
DSS Export Rating Curves= 0
DSS Export Rating Curve Sorted= 0
DSS Export Volume Flow Curves= 0
DXF OffsetX= 0
DXF OffsetY= 0
DXF ScaleX= 0
DXF ScaleY= 0

--- NP11.p01 (plan) ---

Plan Title=Floodplain
Program Version=4.00
Geom File=g01
Flow File=f01
K Sum by GR=0
Std Step Tol=0.01
Critical Tol=0.01
Num of Std Step Trials=20
Max Error Tol=0.3
Flow Tol Ratio=0.001
Split Flow NTrial=30
Split Flow Tol=0.02
Split Flow Ratio=0.02
Log Output Level=0
Friction Slope Method=1
Unsteady Friction Slope Method=2
Unsteady Bridges Friction Slope Method=1
Global Log Level=0
CheckData=False
Run HTab=0
Run UNet=0
Run PostProcess=0
UNET Theta=0
UNET Theta Warmup=0
UNET ZTol=0
UNET ZSATol=0
UNET MxIter=0
UNET MaxInSteps=0
UNET DtIC=0
UNET DtMin=0
UNET MaxCRTS=0
UNET WFStab=0
UNET SFStab=0
UNET WFX=0
UNET SFX=0
UNET DSS MLevel=0
UNET DZMax Abort=0
UNET Convert EG Bridges=0
UNET Use Existing IB Tables=0
UNET Froude Limit=0
UNET Froude Power=0
Write IC File=0
Echo Input=False
Echo Output=False
Write Detailed=0

--- NP11.f01 (steady flow) ---

Flow Title=USGS Regress. Eqn. (2010) - Western-Plateaus
Program Version=4.10
Number of Profiles= 1
Profile Names=P100yr
River Rch & RM=NP11,Main            ,2053.2
     620
River Rch & RM=NP11,Main            ,1756.5
     913
River Rch & RM=NP11,Main            ,242
     940
Boundary for River Rch & Prof#=NP11,Main            , 1
Up Type= 0
Dn Type= 3
Dn Slope=0.00794
DSS Import GetInterval= 0
DSS Import GetPeak= 0
DSS Import FillOption= 0

--- NP11.g01 (geometry) ---

Geom Title=USGS 3m DEM
Program Version=4.10

River Reach=NP11            ,Main
Reach XY= 30
     1714349.839      527062.488     1714442.389      527109.202
     1714477.546      527171.702     1714524.421      527175.609
     1714558.275       527163.89     1714601.244      527113.109
     1714672.858      527063.629     1714732.754      527050.609
     1714813.483      526981.598      1714861.66      526973.786
     1714920.254      526939.931     1715016.608        526920.4
     1715059.577      526887.848     1715085.619      526855.296
     1715116.869      526782.379     1715157.233      526747.223
     1715256.192      526719.879     1715439.785       526726.39
     1715503.587      526669.098     1715504.889       526601.39
     1715495.775      526589.671     1715444.994      526606.598
     1715431.973      526593.577     1715447.598      526486.806
     1715465.827      526467.275     1715559.208      526464.227
     1715670.254      526409.984     1715737.962      526412.588
     1715777.025      526393.056     1715803.238      526366.293

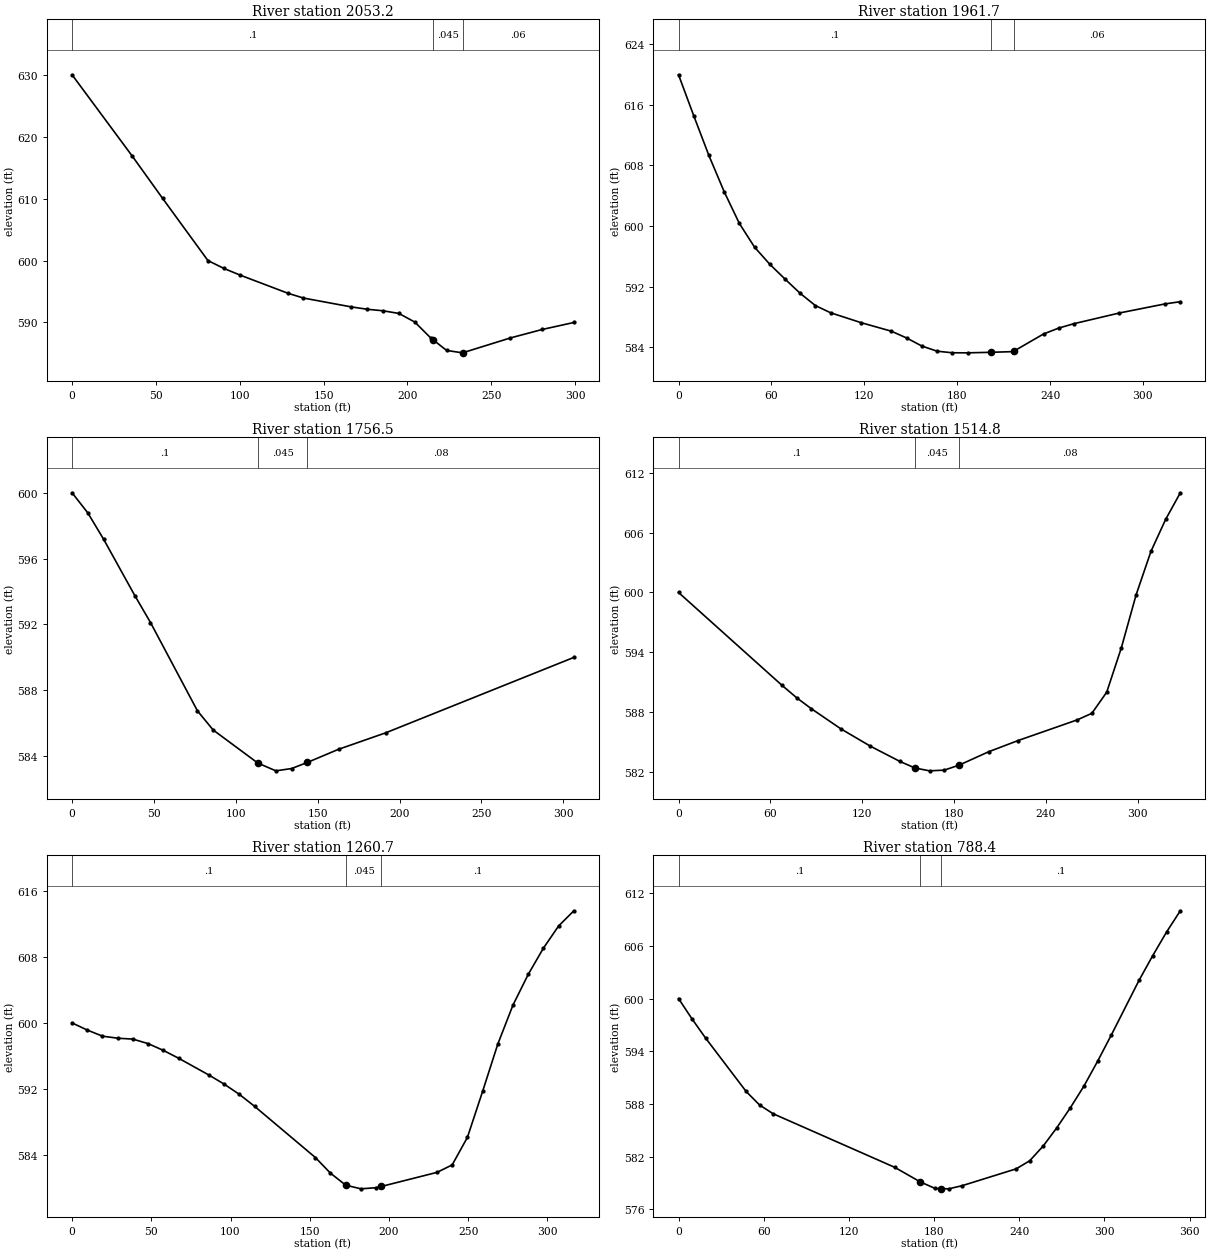
Type RM Length L Ch R = 1 ,2053.2  ,101.2,91.4,85.4
XS GIS Cut Line= 3
     1714234.647      527214.624     1714314.531      527201.129
     1714378.145      526992.386
#Sta/Elev= 20
       0  629.99      36  616.82      54  610.03      81     600    90.5  598.73
     100  597.67   128.5  594.74   137.9  593.95   166.4  592.52   175.9  592.14
   185.4  591.89   194.9  591.46   204.4  590.06   213.8  587.52   215.5  587.16
   223.3  585.49   232.8   585.1   261.3   587.5   280.3  588.87   299.2     590
#Mann= 3 , 0 , 0
       0      .1       0   215.5    .045       0   232.8     .06       0
Bank Sta=215.5,232.8
XS Rating Curve= 0 ,0
Exp/Cntr=0.3,0.1

Type RM Length L Ch R = 1 ,1961.7  ,211.1,205.2,195.2
XS GIS Cut Line= 2
     1714417.173      527313.613     1714448.493      526990.936
#Sta/Elev= 27
       0  619.99     9.8  614.59    19.6  609.33    29.5  604.53    39.3  600.34
    49.1  597.21    58.9  594.96    68.8  592.99    78.6   591.1    88.4  589.49
    98.2  588.54   117.9  587.23   137.5   586.1   147.4   585.2   157.2  584.14
     167  583.46   176.8  583.25   186.7  583.24   201.7  583.31   216.1   583.4
   216.7  583.47   235.8  585.73   245.6  586.51   255.4  587.09   284.9  588.51
   314.4  589.71   324.2     590
#Mann= 3 , 0 , 0
       0      .1       0   201.7    .045       0   216.7     .06       0
Bank Sta=201.7,216.7
XS Rating Curve= 0 ,0
Exp/Cntr=0.3,0.1

Type RM Length L Ch R = 1 ,1756.5  ,240.3,241.8,242
XS GIS Cut Line= 2
     1714632.343      527243.352     1714516.061      526959.747
#Sta/Elev= 14
       0     600     9.6  598.78    19.2  597.19    38.3  593.76    47.9  592.12
    76.6  586.75    86.2  585.59   113.5  583.58   124.5  583.11   134.1  583.25
   143.7  583.62   162.8  584.42   191.6  585.42   306.5     590
#Mann= 3 , 0 , 0
       0      .1       0   113.5    .045       0   143.7     .08       0
Bank Sta=113.5,143.7
XS Rating Curve= 0 ,0
Exp/Cntr=0.3,0.1

Type RM Length L Ch R = 1 ,1514.8  ,255.1,254.1,254
XS GIS Cut Line= 3
     1714842.359      527170.592     1714749.151      526906.812
     1714749.606      526858.647
#Sta/Elev= 21
       0     600    67.5   590.7    77.2  589.44    86.8  588.34   106.1  586.32
   125.4  584.58   144.7  583.05   154.4   582.4     164  582.11   173.6  582.18
   183.3  582.68   202.6  584.02   221.9  585.15   260.5  587.22   270.1  587.88
   279.8     590   289.4  594.47     299  599.76   308.7  604.12   318.3  607.33
   327.9     610
#Mann= 3 , 0 , 0
       0      .1       0   154.4    .045       0   183.3     .08       0
Bank Sta=154.4,183.3
XS Rating Curve= 0 ,0
Exp/Cntr=0.3,0.1

Type RM Length L Ch R = 1 ,1260.7  ,477.9,472.3,467.4
XS GIS Cut Line= 2
     1715078.579      527097.381     1714974.583       526798.25
#Sta/Elev= 28
       0     600     9.6  599.13    19.2  598.39    28.8  598.14    38.4  598.03
      48  597.48    57.6  596.66    67.2  595.71    86.4  593.66      96  592.56
   105.6  591.31   115.2  589.86   153.6  583.63   163.1  581.73   172.7  580.28
   182.3  579.83   191.9  579.97   195.2  580.12   230.3  581.83   239.9  582.74
   249.5  586.08   259.1  591.67   268.7  597.43   278.3  602.18   287.9   605.9
   297.5  609.09   307.1  611.79   316.7  613.63
#Mann= 3 , 0 , 0
       0      .1       0   172.7    .045       0   195.2      .1       0
Bank Sta=172.7,195.2
XS Rating Curve= 0 ,0
Exp/Cntr=0.3,0.1

Type RM Length L Ch R = 1 ,788.4   ,545.7,546.4,532.2
XS GIS Cut Line= 3
     1715482.121      526877.129     1715345.249      526626.597
     1715295.114      526580.597
#Sta/Elev= 24
       0     600     9.5  597.68      19  595.51    47.6  589.42    57.1  587.87
    66.6  586.88   152.3  580.77   170.2  579.12   180.8  578.36   185.2  578.34
   190.3  578.32   199.8  578.68   237.9   580.6   247.4  581.52   256.9   583.2
   266.4  585.26     276  587.55   285.5     590   295.2  592.85   304.9  595.85
   324.4  602.07   334.1   604.9   343.8  607.58   353.5     610
#Mann= 3 , 0 , 0
       0      .1       0   170.2    .045       0   185.2      .1       0
Bank Sta=170.2,185.2
XS Rating Curve= 0 ,0
Exp/Cntr=0.3,0.1

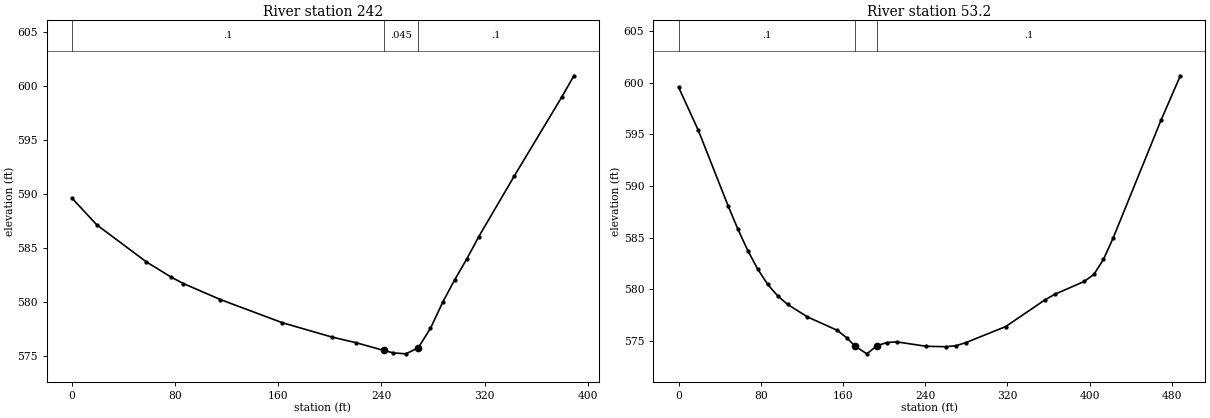
Type RM Length L Ch R = 1 ,242     ,186.1,188.8,191.3
XS GIS Cut Line= 3
      1715724.57      526652.854     1715563.592      526414.536
     1715486.895      526347.856
#Sta/Elev= 21
       0  589.59    19.2  587.13    57.5  583.72    76.7  582.31    86.3  581.71
     115  580.23     163  578.09   201.3  576.77   220.5  576.23   241.9  575.52
   249.2   575.3   258.8  575.21   268.4  575.75     278  577.57   287.6  580.01
   296.8  582.06   306.1  583.97   315.3  586.01     343  591.65     380  598.98
   389.2  600.91
#Mann= 3 , 0 , 0
       0      .1       0   241.9    .045       0   268.4      .1       0
Bank Sta=241.9,268.4
XS Rating Curve= 0 ,0
Exp/Cntr=0.3,0.1

Type RM Length L Ch R = 1 ,53.2    ,60.3,53.2,46.2
XS GIS Cut Line= 3
     1715847.221      526560.606     1715672.497      526227.392
     1715562.877      526203.508
#Sta/Elev= 30
       0  599.56    19.3  595.37    48.2  588.08    57.9  585.78    67.5  583.72
    77.2  581.92    86.8  580.46    96.5  579.35   106.1  578.53   125.4  577.32
   154.4  576.02     164  575.27   171.6   574.5   183.3  573.74     193  574.52
   202.6  574.83   212.2   574.9   241.2  574.47   260.5  574.43   270.1  574.53
   279.8  574.83   318.4  576.38     357  578.99   366.6  579.52   394.9  580.75
   404.3  581.43   413.6  582.89     423  584.95   469.7  596.38   488.4  600.66
#Mann= 3 , 0 , 0
       0      .1       0   171.6    .045       0     193      .1       0
Bank Sta=171.6,193
XS Rating Curve= 0 ,0
Exp/Cntr=0.3,0.1

Chan Stop Cuts=-1
Use User Specified Reach Order=0
Composite Channel Slope=5